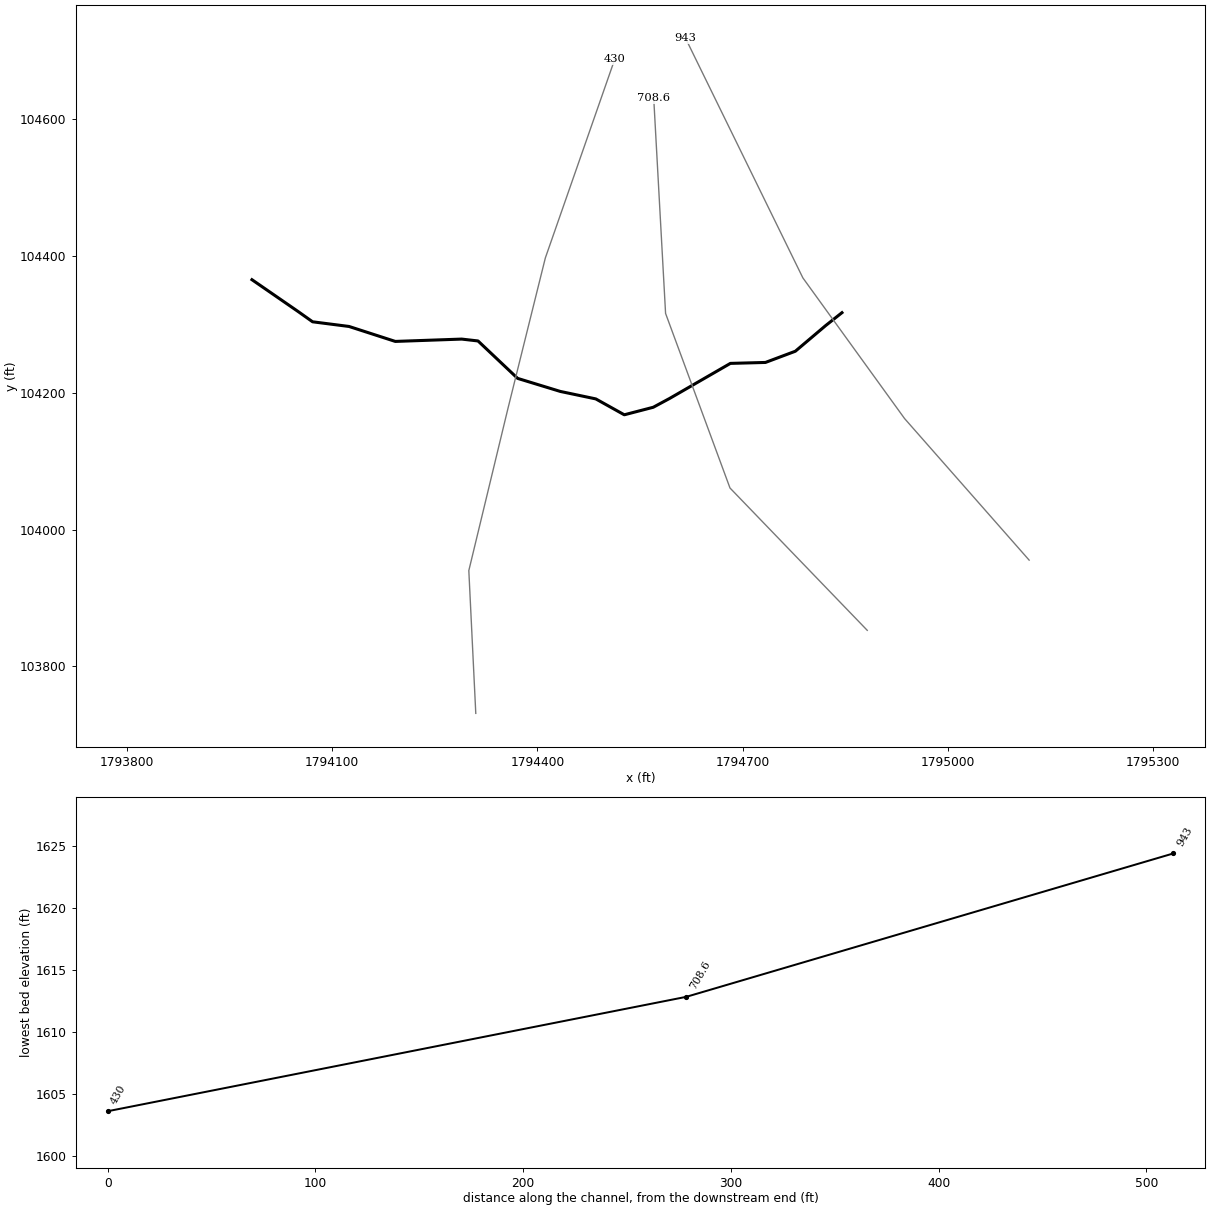
--- Dog Fork.prj (project) ---

Proj Title=Dog Fork
Current Plan=p01
Default Exp/Contr=0,0
English Units
Geom File=g01
Flow File=f01
Plan File=p01
BEGIN DESCRIPTION:
END DESCRIPTION:
DSS Export Rating Curves= 0
DSS Export Rating Curve Sorted= 0
DSS Export Volume Flow Curves= 0
DXF OffsetX= 0
DXF OffsetY= 0
DXF ScaleX= 0
DXF ScaleY= 0

--- Dog Fork.p01 (plan) ---

Plan Title=Floodplain
Program Version=4.00
Geom File=g01
Flow File=f01
K Sum by GR=0
Std Step Tol=0.01
Critical Tol=0.01
Num of Std Step Trials=20
Max Error Tol=0.3
Flow Tol Ratio=0.001
Split Flow NTrial=30
Split Flow Tol=0.02
Split Flow Ratio=0.02
Log Output Level=0
Friction Slope Method=1
Unsteady Friction Slope Method=2
Unsteady Bridges Friction Slope Method=1
Global Log Level=0
CheckData=False
Run HTab=0
Run UNet=0
Run PostProcess=0
UNET Theta=0
UNET Theta Warmup=0
UNET ZTol=0
UNET ZSATol=0
UNET MxIter=0
UNET MaxInSteps=0
UNET DtIC=0
UNET DtMin=0
UNET MaxCRTS=0
UNET WFStab=0
UNET SFStab=0
UNET WFX=0
UNET SFX=0
UNET DSS MLevel=0
UNET DZMax Abort=0
UNET Convert EG Bridges=0
UNET Use Existing IB Tables=0
UNET Froude Limit=0
UNET Froude Power=0
Write IC File=0
Echo Input=False
Echo Output=False
Write Detailed=0

--- Dog Fork.f01 (steady flow) ---

Flow Title=NFF Regression Equation
Program Version=4.00
Number of Profiles=1
Profile Names=P100yr
River Rch & RM=Dog Fork,Main      ,943
576.9506
Boundary for River Rch & Prof#=Dog Fork,Main      ,1
Up Type=0
Dn Type=3
Dn Slope=0.040756

--- Dog Fork.g01 (geometry) ---

Geom Title=USGS 10m DEM
Program Version=4.00

River Reach=Dog Fork        ,Main
Reach XY= 18
     1794845.417      104317.188     1794821.672       104298.39
     1794777.256      104260.807     1794733.523      104244.407
     1794682.274      104243.041     1794593.443      104191.791
     1794569.505      104178.892      1794527.16      104167.875
     1794485.478      104191.108     1794433.545      104202.041
      1794371.21      104221.098      1794313.28       104275.84
     1794289.364      104278.573     1794192.333      104275.157
     1794124.684      104297.023     1794071.385      104303.856
     1794050.202      104318.889     1793982.739      104365.413

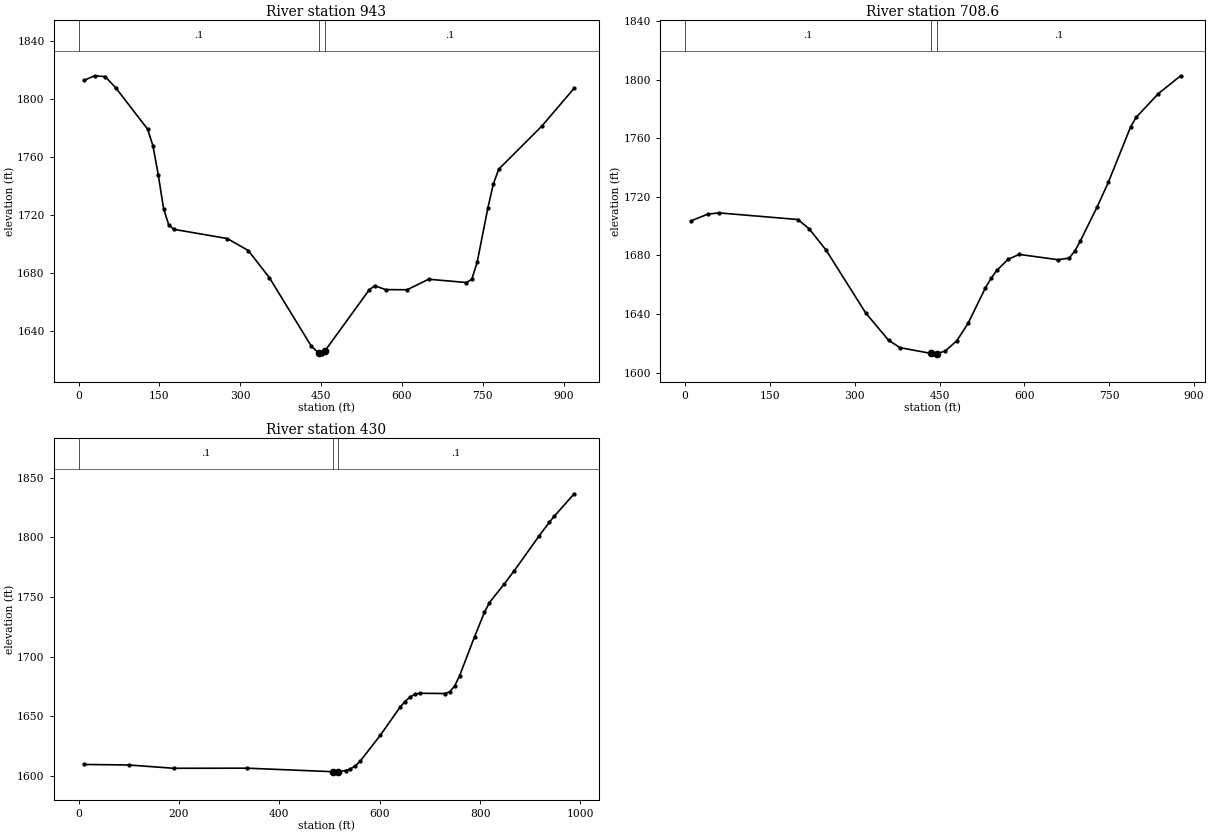
Type RM Length L Ch R = 1 ,943     ,239.9,234.5,229
XS GIS Cut Line= 4
     1795119.084      103955.393     1794936.898      104162.448
     1794788.229      104368.107     1794616.765       104718.31
#Sta/Elev= 30
     9.8 1812.87    29.5 1816.06    49.2 1815.49    68.9 1807.78     128 1779.27
   137.9 1767.79   147.7 1747.97   157.6 1724.55   167.4 1713.01   177.3 1710.19
   275.8 1703.87   314.8 1695.62   353.9 1676.94     432 1629.55   446.5 1624.75
   451.5 1624.41   456.5 1626.18   539.6 1668.71   549.6 1671.33   569.6 1668.68
   609.5 1668.58   649.5 1675.83   719.5 1673.57   729.5 1675.74   739.5  1687.6
   759.5 1725.21   769.5 1741.44   779.5 1751.66   859.5 1781.38   919.5 1807.48
#Mann= 3 , 0 , 0
       0      .1       0   446.5    .045       0   456.5      .1       0
Bank Sta=446.5,456.5
XS Rating Curve= 0 ,0
Exp/Cntr=0.3,0.1

Type RM Length L Ch R = 1 ,708.6   ,290.8,278.5,266.7
XS GIS Cut Line= 4
     1794882.386       103852.72     1794681.683      104060.857
     1794587.525      104316.073     1794570.181      104630.756
#Sta/Elev= 30
      10 1703.53    39.9 1708.17    59.8 1709.06   199.4 1704.52   219.3 1698.26
   249.3 1683.66   319.4 1640.74   359.7 1622.19   379.8  1617.1   435.3 1613.11
   440.3 1612.85   445.3 1612.97   460.4 1614.89   480.6 1621.83   500.7 1633.87
   530.9 1657.74     541 1664.32   551.1 1669.82     571 1677.29   590.7 1680.72
   659.7 1677.07   679.4 1678.23   689.2 1683.09   699.1 1690.04   728.6 1713.08
   748.3 1729.81   787.7 1767.57   797.5 1774.18   836.9 1790.44   876.3 1802.63
#Mann= 3 , 0 , 0
       0      .1       0   435.3    .045       0   445.3      .1       0
Bank Sta=435.3,445.3
XS Rating Curve= 0 ,0
Exp/Cntr=0.3,0.1

Type RM Length L Ch R = 1 ,430     ,437.6,430,422
XS GIS Cut Line= 5
      1794310.01      103731.307     1794299.837      103940.105
     1794357.088      104177.315     1794411.714      104397.197
     1794513.191      104687.746
#Sta/Elev= 30
      10 1609.81    99.5 1609.38   189.1 1606.61   335.9 1606.69   507.2 1603.73
   512.2 1603.63   517.2 1603.78   531.9 1604.75   541.7 1606.09   551.6 1608.66
   561.4  1612.8   600.8 1634.06   640.2 1657.61   650.1 1662.41   659.9 1666.09
   669.8 1668.48   679.6 1669.41   729.3 1669.18   739.2 1670.57   749.1  1675.4
   759.1 1684.07   788.8 1716.65   808.7 1737.26   818.6 1745.32   848.4  1761.1
   868.3 1772.18   917.9 1801.36   937.8 1812.49   947.7  1817.6   987.4 1836.41
#Mann= 3 , 0 , 0
       0      .1       0   507.2    .045       0   517.2      .1       0
Bank Sta=507.2,517.2
XS Rating Curve= 0 ,0
Exp/Cntr=0.3,0.1

Chan Stop Cuts=-1
Use User Specified Reach Order=0